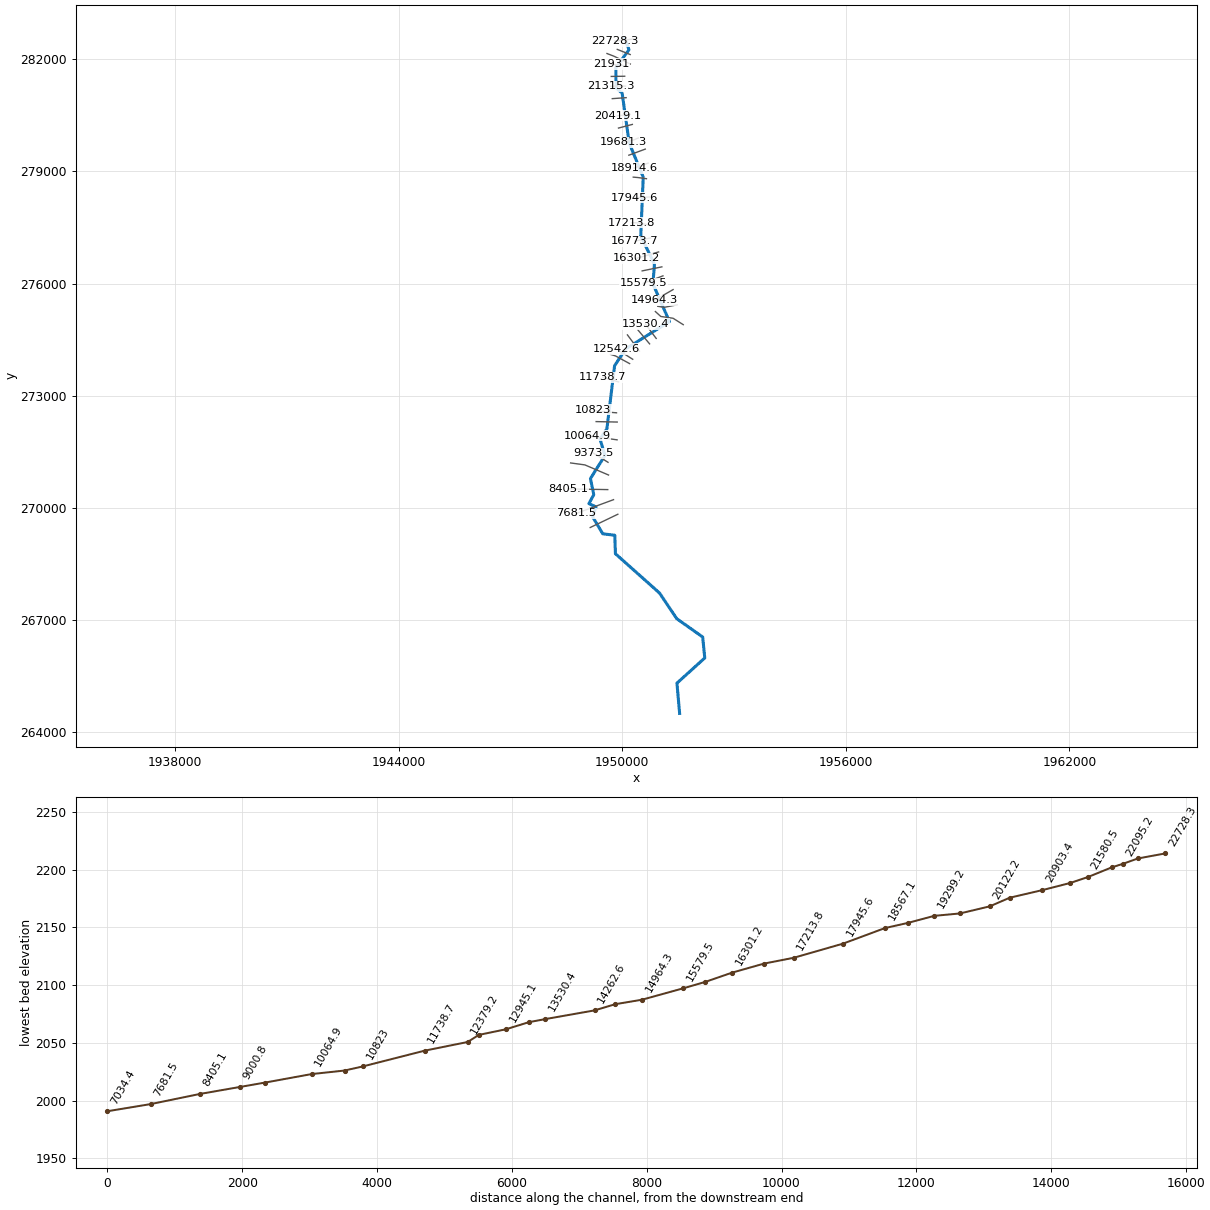
--- HORSSHOERN.prj (project) ---

Proj Title=HORSSHOERN
Current Plan=p01
Geom File=g01
Flow File=f01
Plan File=p01
DSS Export Rating Curves=0
DSS Export Rating Curve Sorted=0
DSS Export Volume Flow Curves=0
DXF OffsetX=0
DXF OffsetY=0
DXF ScaleX=0
DXF ScaleY=0

--- HORSSHOERN.p01 (plan) ---

Plan Title=Floodplain
Program Version=4.00
Geom File=g01
Flow File=f01
K Sum by GR=0
Std Step Tol=0.01
Critical Tol=0.01
Num of Std Step Trials=20
Max Error Tol=0.3
Flow Tol Ratio=0.001
Split Flow NTrial=30
Split Flow Tol=0.02
Split Flow Ratio=0.02
Log Output Level=0
Friction Slope Method=1
Unsteady Friction Slope Method=2
Unsteady Bridges Friction Slope Method=1
Global Log Level=0
CheckData=False
Run HTab=0
Run UNet=0
Run PostProcess=0
UNET Theta=0
UNET Theta Warmup=0
UNET ZTol=0
UNET ZSATol=0
UNET MxIter=0
UNET MaxInSteps=0
UNET DtIC=0
UNET DtMin=0
UNET MaxCRTS=0
UNET WFStab=0
UNET SFStab=0
UNET WFX=0
UNET SFX=0
UNET DSS MLevel=0
UNET DZMax Abort=0
UNET Convert EG Bridges=0
UNET Use Existing IB Tables=0
UNET Froude Limit=0
UNET Froude Power=0
Write IC File=0
Echo Input=False
Echo Output=False
Write Detailed=0

--- HORSSHOERN.f01 (steady flow) ---

Flow Title=NFF Regression Equation
Program Version=4.10
Number of Profiles= 1
Profile Names=P100yr
River Rch & RM=HORSSHOERN,Main            ,22728.3
589.4143
River Rch & RM=HORSSHOERN,Main            ,20903.4
614.9302
River Rch & RM=HORSSHOERN,Main            ,20419.1
666.0338
River Rch & RM=HORSSHOERN,Main            ,18567.1
719.8121
River Rch & RM=HORSSHOERN,Main            ,14568.4
797.1302
River Rch & RM=HORSSHOERN,Main            ,14262.6
1162.614
River Rch & RM=HORSSHOERN,Main            ,9373.5
1228.942
River Rch & RM=HORSSHOERN,Main            ,9000.8
1434.298
River Rch & RM=HORSSHOERN,Main            ,8405.1
1592.904
Boundary for River Rch & Prof#=HORSSHOERN,Main            , 1
Up Type= 0
Dn Type= 3
Dn Slope=0.01151
DSS Import GetInterval= 0
DSS Import GetPeak= 0
DSS Import FillOption= 0

--- HORSSHOERN.g01 (geometry) ---

Geom Title=USGS 10m DEM
Program Version=4.10

River Reach=HORSSHOERN      ,Main
Reach XY= 30
     1950069.001      282555.865     1950180.262      282251.295
     1949826.018      281763.907     1949834.328       281229.34
     1949997.347      281090.144     1950185.918      279760.414
     1950562.906       278843.92     1950496.301      277272.472
     1950863.964       276515.61     1950823.112      275991.868
     1951267.372      274982.348      1950088.23      274249.464
     1949793.904      273799.468     1949588.086      272115.208
      1949403.19      271844.375     1949535.037      271399.885
     1949145.704      270783.996     1949235.711      270352.672
     1949104.883      270115.083     1949295.444      270026.691
     1949204.756        269762.2      1949477.97      269306.919
     1949799.683      269268.291     1949816.709      268774.547
     1951000.397      267723.191     1951462.107      267038.088
      1952158.46      266547.679     1952214.286       265987.28
     1951467.769      265313.734     1951539.659      264505.686

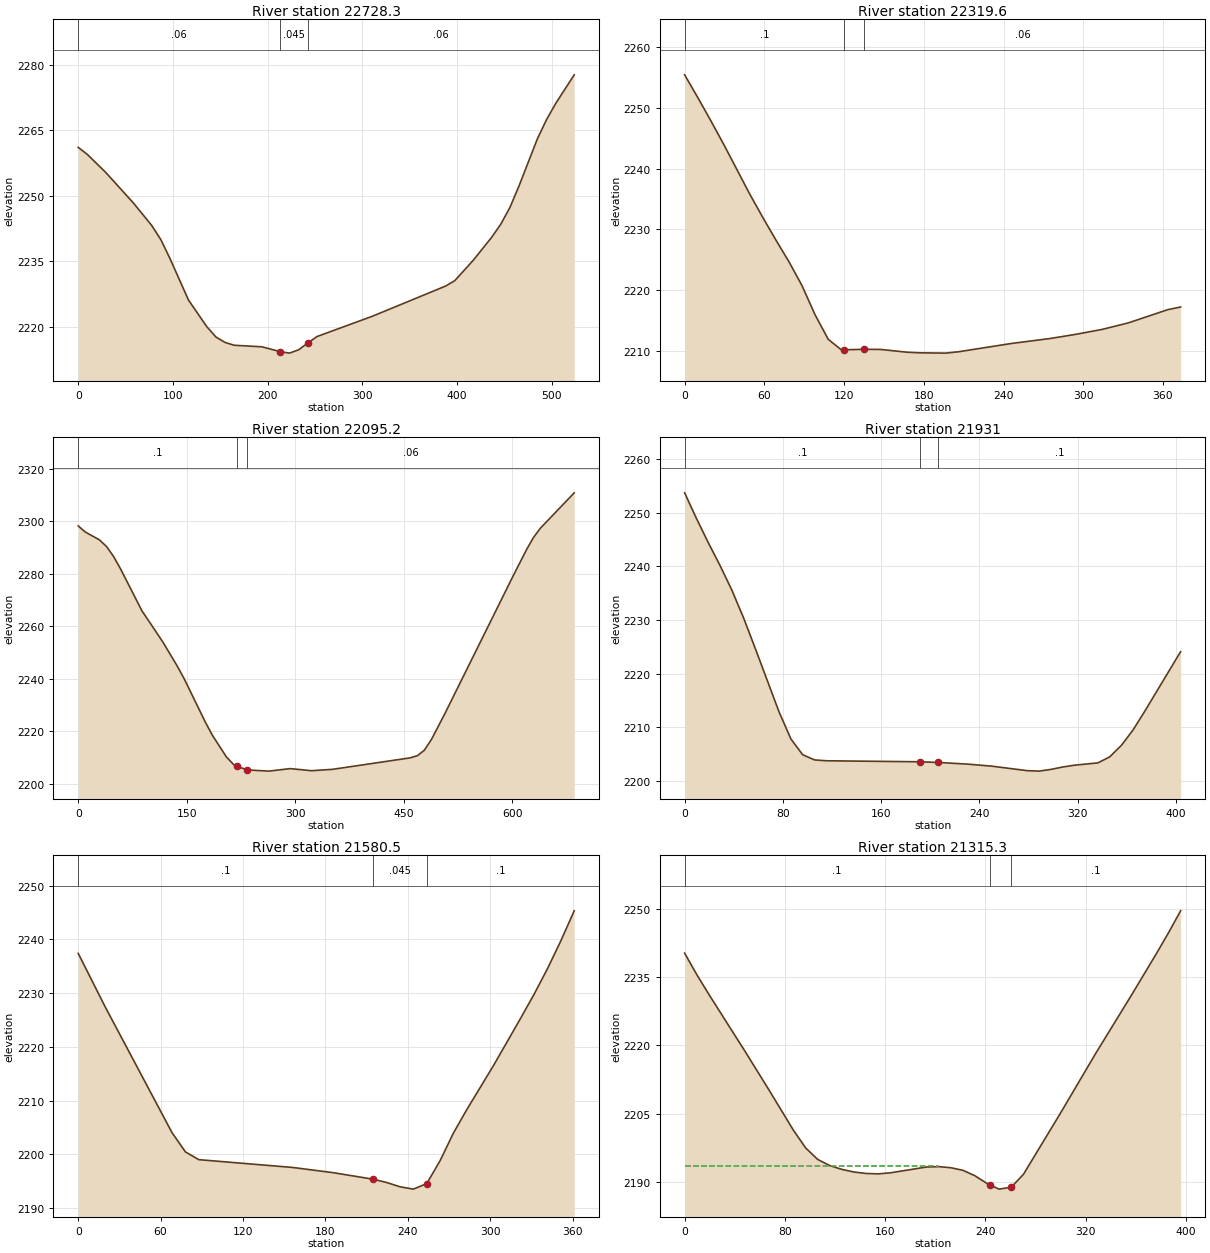
Type RM Length L Ch R = 1 ,22728.3 ,420.1,408.7,397.1
XS GIS Cut Line= 2
     1950311.839      282538.123     1949791.006      282484.304
#Sta/Elev= 30
       0  2261.1     9.7 2259.48    29.1 2255.35    58.2 2248.37    77.6 2243.21
    87.3 2239.94      97 2235.57   116.4 2226.13   135.8    2220   145.4 2217.65
   155.1  2216.4   164.8 2215.76   193.9 2215.41   213.3  2214.3     223 2213.96
   232.7 2214.72   242.6 2216.32   252.1 2217.76   310.3 2222.39   387.9 2229.33
   397.6 2230.58     417 2235.23   436.3 2240.45     446 2243.46   455.7 2247.31
   465.4  2252.3   484.8  2263.1   494.5  2267.5   504.2 2271.21   523.6 2277.72
#Mann= 3 , 0 , 0
       0     .06       0   213.3    .045       0   242.6     .06       0
Bank Sta=213.3,242.6
XS Rating Curve= 0 ,0
Exp/Cntr=0.3,0.1

Type RM Length L Ch R = 1 ,22319.6 ,225.9,224.4,222.7
XS GIS Cut Line= 2
      1950213.83       282122.95     1949866.607      282260.103
#Sta/Elev= 26
       0 2255.47     9.8 2251.77    19.6 2247.95    29.5 2243.97    49.1 2235.77
      59 2231.89    68.8 2228.19    78.6 2224.62    88.4 2220.68    98.2 2215.89
   108.1 2211.85   117.9 2210.12   120.1 2210.12   135.1  2210.2   147.4 2210.18
     167 2209.73   176.8 2209.62   196.5 2209.57   206.3  2209.8   245.6 2211.15
   275.1 2211.98   294.7 2212.68   314.4 2213.49     334 2214.56   363.5 2216.73
   373.3 2217.18
#Mann= 3 , 0 , 0
       0      .1       0   120.1    .045       0   135.1     .06       0
Bank Sta=120.1,135.1
XS Rating Curve= 0 ,0
Exp/Cntr=0.3,0.1

Type RM Length L Ch R = 1 ,22095.2 ,154.5,164.2,173.7
XS GIS Cut Line= 3
     1950215.434      281868.811     1949774.686      282078.748
     1949590.659      282149.929
#Sta/Elev= 30
       0 2298.31     9.8 2295.98    29.3    2293    39.1 2290.48    48.8  2286.7
    58.6  2281.9    87.9 2266.05   117.2 2253.99   136.7 2244.99   146.5 2240.06
   175.8 2223.51   185.5 2218.53     205 2210.23   214.8  2207.4   218.8 2206.78
   233.8 2205.34   263.6 2204.89   292.9 2205.85   322.2 2205.05   351.5 2205.57
   458.9 2209.95   468.7 2210.76   478.4 2212.86   488.2 2216.96     507 2226.93
   600.9 2279.16   619.7 2289.32   629.1 2293.85   638.5 2297.36   685.5 2310.92
#Mann= 3 , 0 , 0
       0      .1       0   218.8    .045       0   233.8     .06       0
Bank Sta=218.8,233.8
XS Rating Curve= 0 ,0
Exp/Cntr=0.3,0.1

Type RM Length L Ch R = 1 ,21931   ,362.9,350.5,351
XS GIS Cut Line= 2
     1950099.246      281820.867     1949698.205      281867.742
#Sta/Elev= 27
       0 2253.72     9.6 2248.96    19.2 2244.46    28.8 2240.18    38.4 2235.62
    48.1 2230.35    57.7  2224.6    76.9 2212.87    86.5 2207.85    96.1  2204.9
   105.8 2203.93   115.4 2203.77   191.6 2203.58   206.6 2203.46   230.7 2203.14
     250 2202.77   278.8 2201.93   288.4 2201.84     298 2202.15   307.6  2202.6
   317.2 2202.94   336.5 2203.38   346.1  2204.5   355.7 2206.67   365.3 2209.59
   374.9 2213.11   403.8 2224.11
#Mann= 3 , 0 , 0
       0      .1       0   191.6    .045       0   206.6      .1       0
Bank Sta=191.6,206.6
XS Rating Curve= 0 ,0
Exp/Cntr=0.3,0.1

Type RM Length L Ch R = 1 ,21580.5 ,265.4,265.1,264.7
XS GIS Cut Line= 2
     1950066.353       281542.29     1949705.242      281537.082
#Sta/Elev= 21
       0 2237.38    19.5  2227.5    68.3 2204.04    78.1 2200.45    87.8 2199.01
   156.2 2197.56   185.4  2196.6   214.7 2195.38   224.5 2194.77   234.3 2193.97
     244 2193.53   253.8 2194.55   263.5 2198.81   273.3 2203.99   283.1 2208.37
   302.6 2216.59   322.1 2225.27   331.9 2229.73   341.6 2234.46   351.4 2239.67
   361.2 2245.29
#Mann= 3 , 0 , 0
       0      .1       0   214.7    .045       0   253.8      .1       0
Bank Sta=214.7,253.8
XS Rating Curve= 0 ,0
Exp/Cntr=0.3,0.1

Type RM Length L Ch R = 1 ,21315.3 ,411.6,412,410.3
XS GIS Cut Line= 2
     1950088.753      281279.106     1949692.892      281275.285
#Sta/Elev= 30
       0 2240.33     9.7 2235.61    19.3 2231.28    48.3 2218.67    67.6 2210.08
    86.9  2201.3    96.6 2197.43   106.2  2194.9   115.9 2193.53   125.5  2192.7
   135.2 2192.12   144.8  2191.8   154.5 2191.71   164.2 2191.94   193.1 2193.22
   202.8  2193.3   212.4 2193.07   222.1  2192.5   231.7  2191.3   241.4 2189.59
   243.4 2189.33     251 2188.35   260.7 2188.77   270.4 2191.59   299.3 2204.76
   328.3 2218.32   357.3 2231.36   376.6 2240.24   386.2  2244.8   395.9 2249.65
#Mann= 3 , 0 , 0
       0      .1       0   243.4    .045       0   260.7      .1       0
#XS Ineff= 2 , 0
          202.25 2193.42
Permanent Ineff=
       F       F
Bank Sta=243.4,260.7
XS Rating Curve= 0 ,0
Exp/Cntr=0.3,0.1

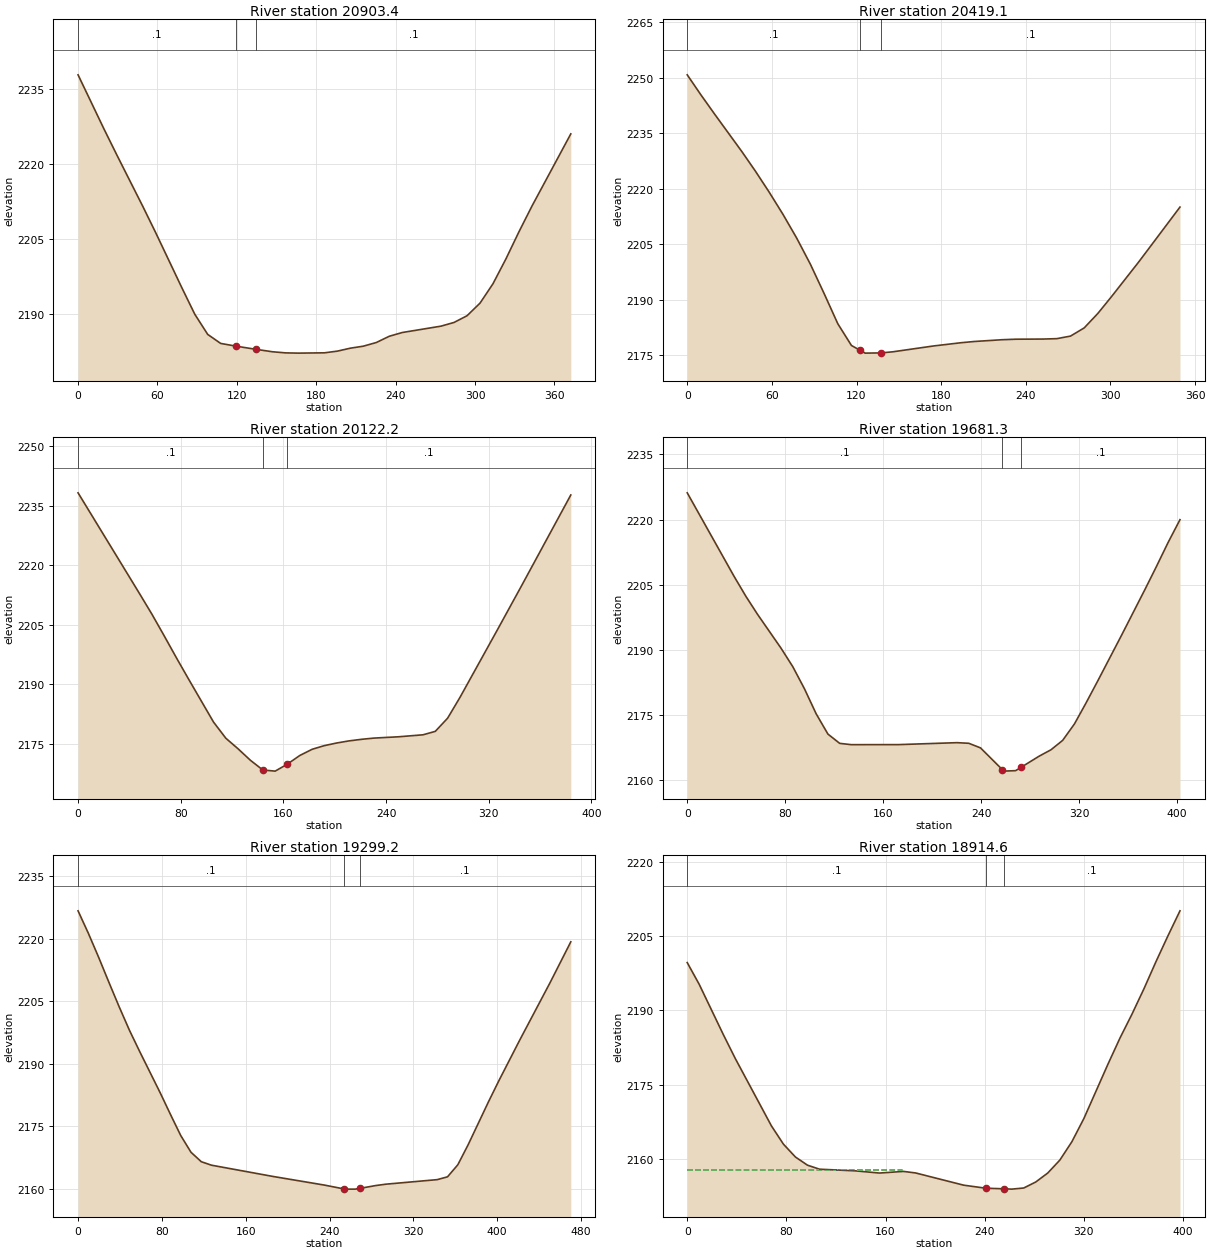
Type RM Length L Ch R = 1 ,20903.4 ,482.5,484.3,485.6
XS GIS Cut Line= 2
     1950104.547      280969.373      1949733.02      280943.332
#Sta/Elev= 30
       0 2237.85    19.6 2227.02    29.4 2221.78      49 2211.51    58.8 2206.22
    78.4  2195.3    88.2 2189.99      98 2185.94   107.8 2184.14   119.7 2183.58
   134.7 2182.95     147 2182.47   156.8 2182.25   166.6  2182.2   186.2 2182.26
     196  2182.6   205.8 2183.19   215.6 2183.59   225.4 2184.32   235.2 2185.57
     245 2186.32   274.4  2187.6   284.2 2188.34     294 2189.68   303.8  2192.2
   313.6 2196.08   323.4 2201.06   333.2 2206.45     343 2211.58   372.4 2226.04
#Mann= 3 , 0 , 0
       0      .1       0   119.7    .045       0   134.7      .1       0
Bank Sta=119.7,134.7
XS Rating Curve= 0 ,0
Exp/Cntr=0.3,0.1

Type RM Length L Ch R = 1 ,20419.1 ,293,296.9,300
XS GIS Cut Line= 2
     1950211.752      280521.457      1949864.53      280483.262
#Sta/Elev= 29
       0 2250.78     9.7 2245.37    19.4 2240.18    38.8 2230.01    48.5 2224.67
    58.2 2219.03    67.9 2213.08    77.6 2206.68    87.3 2199.63      97 2191.74
   106.7 2183.58   116.4 2177.68   122.2 2176.44   126.1 2175.61   137.2 2175.67
   145.6 2175.96   174.7 2177.55   194.1 2178.42   203.8 2178.76   223.2 2179.23
   232.9 2179.37   252.3 2179.41     262 2179.52   271.7 2180.21   281.4 2182.42
   291.1 2186.34   300.8 2190.89   320.2 2200.31   349.3 2215.06
#Mann= 3 , 0 , 0
       0      .1       0   122.2    .045       0   137.2      .1       0
Bank Sta=122.2,137.2
XS Rating Curve= 0 ,0
Exp/Cntr=0.3,0.1

Type RM Length L Ch R = 1 ,20122.2 ,440.3,440.9,441.1
XS GIS Cut Line= 2
      1950270.78      280254.095     1949899.252      280156.873
#Sta/Elev= 28
       0 2238.25      48 2212.81    57.6 2207.65    67.2 2202.18    76.8  2196.6
    86.4 2191.17   105.6 2180.48   115.2 2176.41   124.8 2173.73   134.4 2170.84
     144 2168.42   153.6 2168.13   162.9 2169.84   172.8 2172.07   182.4 2173.63
     192 2174.56   201.6 2175.22   211.2 2175.75   220.8 2176.14   230.4 2176.45
   249.6 2176.78   268.8 2177.28   278.4 2178.15     288 2181.47   297.6 2186.69
   326.4  2203.5   345.6 2214.82     384 2237.71
#Mann= 3 , 0 , 0
       0      .1       0     144    .045       0   162.9      .1       0
Bank Sta=144,162.9
XS Rating Curve= 0 ,0
Exp/Cntr=0.3,0.1

Type RM Length L Ch R = 1 ,19681.3 ,376.6,382,386.9
XS GIS Cut Line= 3
      1950427.03      279889.512     1950312.447      279840.901
     1950041.613      279778.401
#Sta/Elev= 30
       0 2226.15    38.3 2206.88    47.9  2202.3    57.4 2198.15    76.6 2190.34
    86.2 2186.08    95.7    2181   105.3 2175.21   114.9 2170.54   124.5  2168.4
     134  2168.1   172.4 2168.11   220.3 2168.56   229.9 2168.42   239.5 2167.36
   257.4 2162.33   258.6    2162   268.2 2162.11   272.4 2162.84   287.4 2165.45
     297 2166.91   306.6 2169.09   316.2 2172.87   325.7 2177.72   335.3 2182.82
   354.5 2193.22   373.7 2203.82   383.2 2209.19   392.8 2214.76   402.4 2219.96
#Mann= 3 , 0 , 0
       0      .1       0   257.4    .045       0   272.4      .1       0
Bank Sta=257.4,272.4
XS Rating Curve= 0 ,0
Exp/Cntr=0.3,0.1

Type RM Length L Ch R = 1 ,19299.2 ,389.1,384.7,383.7
XS GIS Cut Line= 2
     1950618.002      279594.373      1950177.03      279431.179
#Sta/Elev= 30
       0 2226.71     9.8 2221.34    19.6 2215.59    29.4 2209.58    39.2  2203.7
      49 2198.07    58.8 2192.95    78.4 2183.03    88.2 2177.84      98 2172.78
   107.8 2168.76   117.6  2166.5   127.4 2165.66   186.1 2162.96   235.1 2160.89
   253.7 2159.97   254.7 2159.92   264.5 2159.92   268.7 2160.09   284.1 2160.78
   293.9 2161.11   342.8  2162.2   352.6 2162.88   362.4 2165.77   372.2 2170.55
   391.8 2180.96   401.6 2185.96   421.2 2195.56   450.6 2209.56   470.2 2219.27
#Mann= 3 , 0 , 0
       0      .1       0   253.7    .045       0   268.7      .1       0
Bank Sta=253.7,268.7
XS Rating Curve= 0 ,0
Exp/Cntr=0.3,0.1

Type RM Length L Ch R = 1 ,18914.6 ,359.2,347.5,335.8
XS GIS Cut Line= 2
     1950697.863      279219.373     1950322.863      279087.429
#Sta/Elev= 30
       0 2199.68     9.7 2195.27    29.1 2185.14    38.8 2180.28    67.9 2166.69
    77.6 2162.99    87.3 2160.39      97 2158.74   106.7 2157.93   135.7 2157.59
   155.1 2157.15   174.5 2157.48   184.2 2157.17     223  2154.7   240.7 2154.09
   255.7 2153.96   261.8  2153.9   271.5 2154.13   281.2 2155.35   290.9 2157.17
   300.6 2159.77   310.3 2163.48     320 2168.18   339.4 2179.15   349.1 2184.43
   358.8 2189.27   368.4 2194.37   378.1 2199.85   387.8 2205.09   397.5 2210.14
#Mann= 3 , 0 , 0
       0      .1       0   240.7    .045       0   255.7      .1       0
#XS Ineff= 2 , 0
          173.52 2157.72
Permanent Ineff=
       F       F
Bank Sta=240.7,255.7
XS Rating Curve= 0 ,0
Exp/Cntr=0.3,0.1

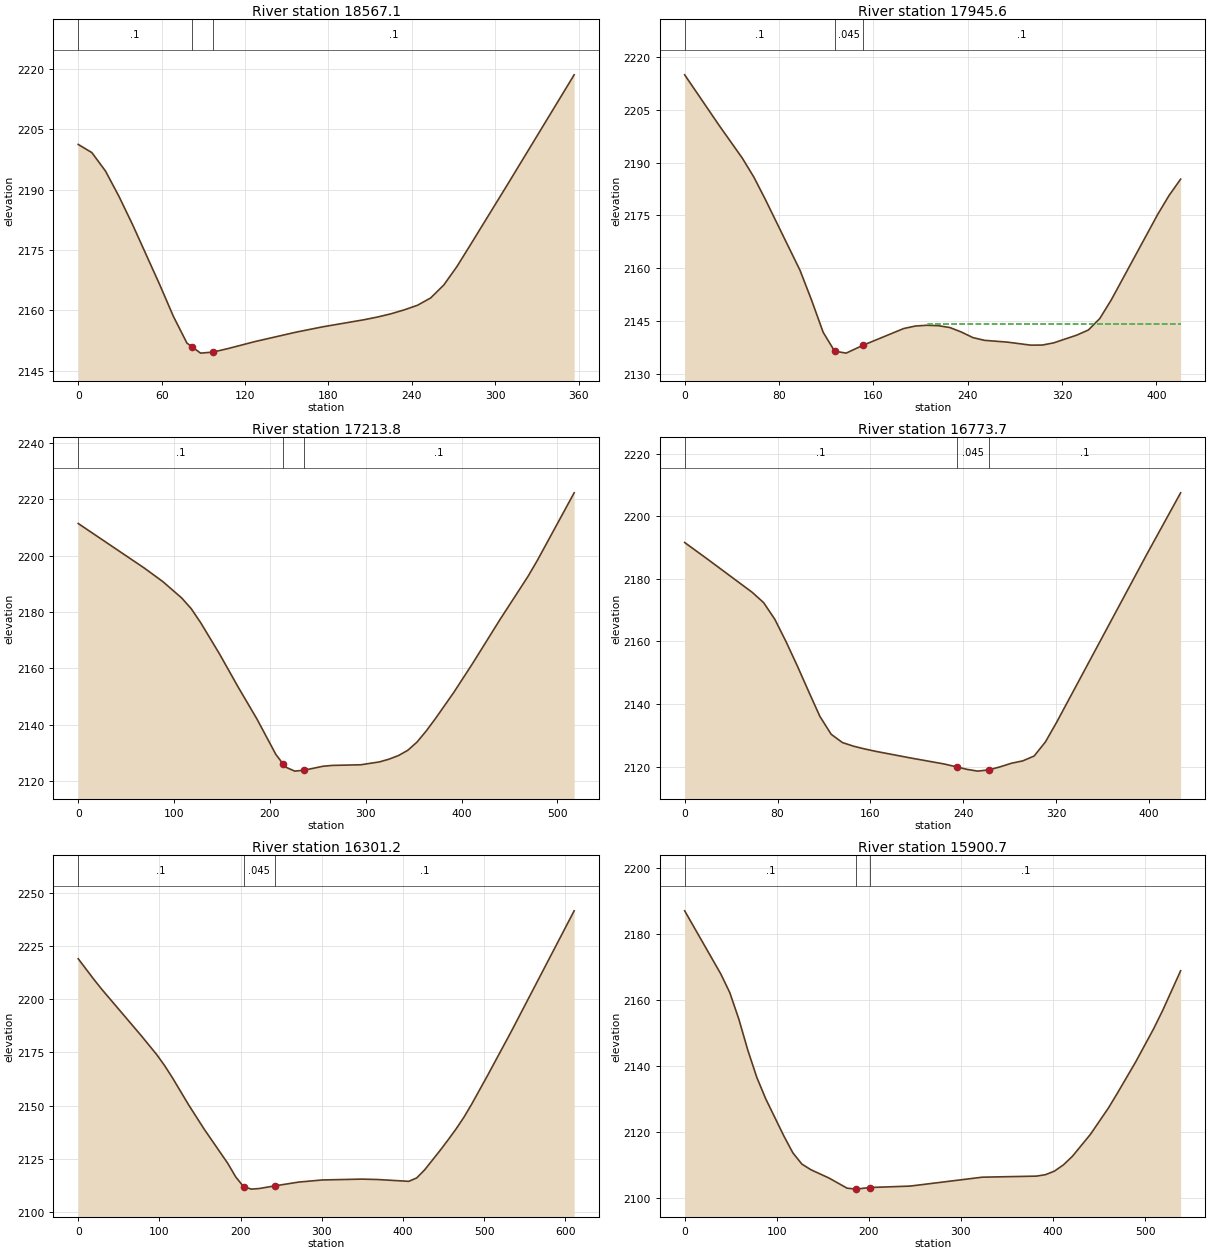
Type RM Length L Ch R = 1 ,18567.1 ,617.1,621.5,625.3
XS GIS Cut Line= 3
     1950649.252      278802.707     1950416.613      278833.957
     1950295.086      278844.373
#Sta/Elev= 26
       0 2201.21     9.8 2199.18    19.6  2194.6    29.3  2188.3    39.1 2181.27
    58.7 2166.28    68.5 2158.43    78.2 2151.82      82 2150.85      88 2149.32
      97 2149.58   107.6 2150.44   127.1 2152.19   156.5 2154.52     176 2155.87
   205.4 2157.61   215.2 2158.29     225  2159.1   234.7  2160.1   244.1 2161.23
   253.5 2163.04   262.9 2166.24   272.3  2170.8   281.6 2175.96   309.8 2191.82
   356.7 2218.51
#Mann= 3 , 0 , 0
       0      .1       0      82    .045       0      97      .1       0
Bank Sta=82,97
XS Rating Curve= 0 ,0
Exp/Cntr=0.3,0.1

Type RM Length L Ch R = 1 ,17945.6 ,736.2,731.8,726.7
XS GIS Cut Line= 2
      1950739.53      278313.123     1950319.391      278295.762
#Sta/Elev= 30
       0 2214.96    29.3 2200.55    48.9 2191.27    58.7 2185.87    68.4 2179.54
    97.8  2159.4   107.6 2150.92   117.4  2141.8   127.1 2136.43   136.9 2135.86
   151.4 2138.12   185.8 2142.86   195.6 2143.56   205.4 2143.78   215.1 2143.66
   224.9 2143.13   234.7 2141.84   244.5 2140.26   254.2  2139.5   273.8 2138.98
   293.4 2138.13   303.2 2138.15   312.9 2138.78   332.5 2140.98   342.3 2142.44
     352 2145.71   361.8 2151.05   400.9 2175.19   410.7 2180.67   420.5 2185.31
#Mann= 3 , 0 , 0
       0      .1       0   127.1    .045       0   151.4      .1       0
#XS Ineff= 2 , 0
                          206.34            2144
Permanent Ineff=
       F       F
Bank Sta=127.1,151.4
XS Rating Curve= 0 ,0
Exp/Cntr=0.3,0.1

Type RM Length L Ch R = 1 ,17213.8 ,431,440.2,449.4
XS GIS Cut Line= 3
     1950767.308      277552.707     1950430.502      277622.151
     1950256.891      277625.623
#Sta/Elev= 30
       0 2211.41    68.8 2195.65    88.4 2190.78   108.1 2184.96   117.9 2181.21
   127.7 2176.29   147.4 2165.19     167 2153.36   186.7 2141.98   206.3  2129.5
   213.9  2126.1   216.2 2125.07     226 2123.61   235.8 2123.95   255.5 2125.34
   265.3 2125.64   294.8 2125.86   314.4 2126.89   324.2 2127.84   334.1 2129.12
   343.9 2130.99   353.5  2133.9   363.2 2137.87   372.8 2142.26   392.1 2151.62
   411.4 2161.71   440.4  2177.5   469.3 2192.63     479 2198.26   517.5 2222.28
#Mann= 3 , 0 , 0
       0      .1       0   213.9    .045       0   235.8      .1       0
Bank Sta=213.9,235.8
XS Rating Curve= 0 ,0
Exp/Cntr=0.3,0.1

Type RM Length L Ch R = 1 ,16773.7 ,470.4,472.5,474.3
XS GIS Cut Line= 2
     1950759.229      277218.466     1950340.356      277134.692
#Sta/Elev= 28
       0 2191.59    19.4 2186.36    58.2 2175.68      68  2172.4    77.7 2167.05
    87.4 2159.87    97.1 2152.14   106.8 2144.01   116.5 2136.05   126.2 2130.36
   135.9 2127.71   145.6 2126.54   155.3 2125.65     165 2124.88   194.2 2122.82
   223.3 2120.89   234.3 2119.94   242.7 2119.19   252.4 2118.59   262.1 2118.99
   271.8 2119.97   281.5 2121.11   291.2 2121.86     301 2123.41   310.7 2127.89
   320.4 2134.19     398 2187.79   427.2 2207.46
#Mann= 3 , 0 , 0
       0      .1       0   234.3    .045       0   262.1      .1       0
Bank Sta=234.3,262.1
XS Rating Curve= 0 ,0
Exp/Cntr=0.3,0.1

Type RM Length L Ch R = 1 ,16301.2 ,402.4,400.5,398.5
XS GIS Cut Line= 2
     1950975.641      276844.373     1950388.836      276674.234
#Sta/Elev= 30
       0 2218.95    19.4 2209.21    29.1 2204.58    77.6 2182.86      97 2173.81
   106.7 2168.65   116.4 2162.88   135.8  2150.5   155.2 2138.94   184.3 2122.86
     194 2116.55   203.7 2111.94   213.4 2110.78     223 2111.06   242.4 2112.32
   271.5 2114.08   300.6 2115.08   349.1 2115.48   368.5  2115.3   407.3 2114.44
     417 2116.03   426.7 2119.78   446.1 2129.06   455.8 2133.96   465.5 2139.02
   475.2 2144.54   484.9 2150.78   504.3 2164.13   533.4  2184.7     611 2241.45
#Mann= 3 , 0 , 0
       0      .1       0   203.7    .045       0   242.4      .1       0
Bank Sta=203.7,242.4
XS Rating Curve= 0 ,0
Exp/Cntr=0.3,0.1

Type RM Length L Ch R = 1 ,15900.7 ,312.7,321.2,326
XS GIS Cut Line= 2
     1951062.447      276445.068     1950534.669      276337.429
#Sta/Elev= 30
       0  2187.1    39.2 2167.98      49  2162.3    58.8 2154.29    68.6 2144.83
    78.4 2136.56    88.1 2130.06   107.7 2118.84   117.5 2113.72   127.3 2110.31
   137.1  2108.6   156.7 2106.09   176.3 2103.02   186.1 2102.72   186.3 2102.73
   201.3 2103.21   244.8 2103.64   323.2 2106.34     382 2106.66   391.7 2107.09
   401.5 2108.17   411.3 2110.07   421.1 2112.68   440.7 2119.35   460.3 2127.36
   470.1 2131.89   489.7 2141.24   509.3 2151.35   519.1 2156.89   538.6 2168.92
#Mann= 3 , 0 , 0
       0      .1       0   186.3    .045       0   201.3      .1       0
Bank Sta=186.3,201.3
XS Rating Curve= 0 ,0
Exp/Cntr=0.3,0.1

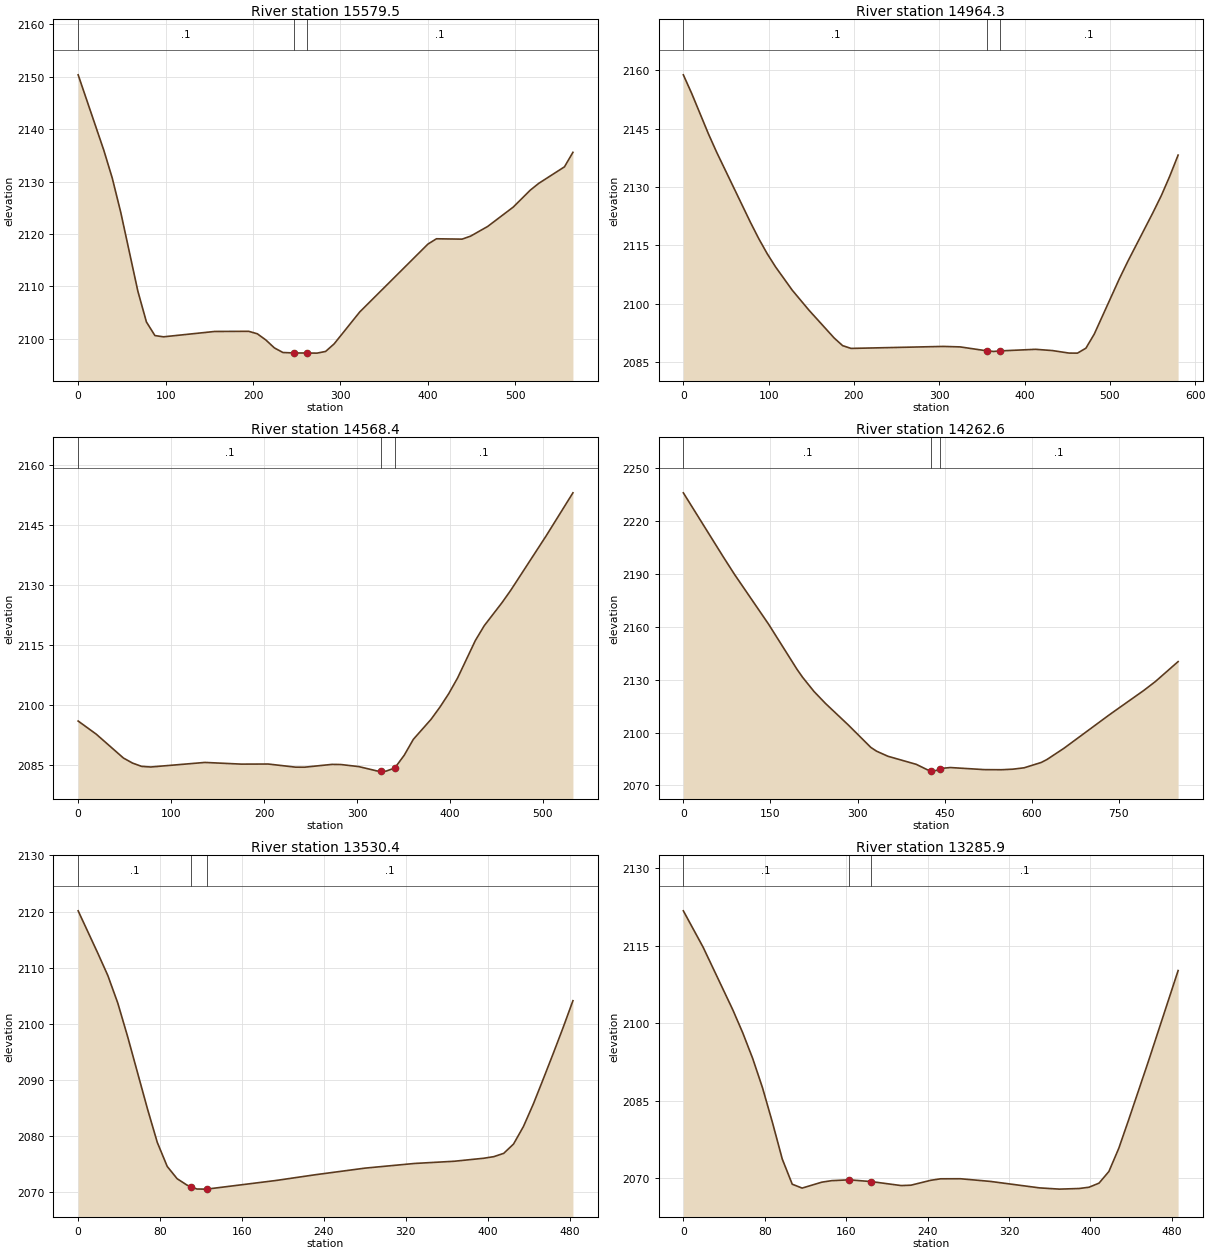
Type RM Length L Ch R = 1 ,15579.5 ,615.9,615.2,618
XS GIS Cut Line= 2
      1951092.17      276204.749     1950562.656      276005.096
#Sta/Elev= 30
       0 2150.35    29.3 2135.99      39 2130.66    48.8 2124.07    68.3 2109.08
    78.1 2103.21    87.8 2100.62    97.6 2100.38   156.1  2101.4   195.1 2101.43
   204.9 2100.96   214.6 2099.79   224.4 2098.27   234.2 2097.39   246.5  2097.3
   261.5 2097.29   273.2 2097.27     283 2097.59   292.7 2099.02     322 2105.11
     400 2118.06   409.8 2119.08   439.1 2119.01   448.8 2119.58   468.3 2121.42
   497.6 2125.12   517.1 2128.35   526.9 2129.66   556.2  2132.8   565.9 2135.57
#Mann= 3 , 0 , 0
       0      .1       0   246.5    .045       0   261.5      .1       0
Bank Sta=246.5,261.5
XS Rating Curve= 0 ,0
Exp/Cntr=0.3,0.1

Type RM Length L Ch R = 1 ,14964.3 ,378.8,396,389.3
XS GIS Cut Line= 2
      1951364.53      275837.429     1950861.058      275549.234
#Sta/Elev= 30
       0 2158.83     9.8 2154.05    29.5 2143.62    39.3 2138.84    78.7 2120.93
    88.5 2116.72    98.3 2112.89   108.2 2109.47   127.8 2103.48   147.5 2098.32
     177 2091.19   186.8 2089.26   196.6 2088.55   304.8 2089.06   324.5 2088.94
   356.4 2087.91   363.8 2087.77   371.4 2087.91     413 2088.32   432.6    2088
   452.3 2087.35   462.1 2087.34     472 2088.61   481.8 2092.24   511.3 2106.49
   521.1  2110.9   550.6 2123.44   560.5 2127.85   570.3  2132.8   580.1 2138.21
#Mann= 3 , 0 , 0
       0      .1       0   356.4    .045       0   371.4      .1       0
Bank Sta=356.4,371.4
XS Rating Curve= 0 ,0
Exp/Cntr=0.3,0.1

Type RM Length L Ch R = 1 ,14568.4 ,312.7,305.8,298.8
XS GIS Cut Line= 3
     1951475.821      275430.295     1951121.654      275362.587
     1950952.383      275391.232
#Sta/Elev= 30
       0 2095.98    19.5  2092.7    48.7 2086.75    58.5 2085.49    68.2 2084.67
      78 2084.51   136.4 2085.65   175.4 2085.23   204.6 2085.25   233.9 2084.47
   243.6 2084.46   272.9 2085.16   282.6 2085.13   302.1  2084.6   321.6 2083.52
   325.7  2083.5   331.3 2083.48   340.7 2084.27   350.8 2087.45   360.6 2091.41
   379.7 2096.42   389.2 2099.45   398.7 2102.82   408.3 2106.77   427.3 2116.07
   436.9 2119.78     456 2125.53   465.5 2128.65   503.6 2142.24   532.3 2152.94
#Mann= 3 , 0 , 0
       0      .1       0   325.7    .045       0   340.7      .1       0
Bank Sta=325.7,340.7
XS Rating Curve= 0 ,0
Exp/Cntr=0.3,0.1

Type RM Length L Ch R = 1 ,14262.6 ,746.7,732.2,715.9
XS GIS Cut Line= 4
     1951637.279      274899.045     1951363.841       275070.92
     1951034.669      275118.679     1950888.836      275250.623
#Sta/Elev= 30
       0 2235.79    68.5 2199.67    88.1  2189.6   146.8 2161.39   195.7 2135.86
   205.5 2131.26   225.1 2123.24   244.7 2116.51   283.8 2104.38     323 2091.55
   332.8 2089.43   352.3 2086.56   401.2 2081.97   420.8 2078.82   427.4 2078.36
   430.6 2078.13   442.4 2079.09   450.2 2079.86   459.9 2080.16   518.6 2078.98
     548 2078.92   567.5 2079.23   587.1 2080.02   616.5 2083.05   626.2 2084.69
   655.6 2091.08   734.2 2110.15   793.2 2123.87   812.9 2128.84   852.2 2140.18
#Mann= 3 , 0 , 0
       0      .1       0   427.4    .045       0   442.4      .1       0
Bank Sta=427.4,442.4
XS Rating Curve= 0 ,0
Exp/Cntr=0.3,0.1

Type RM Length L Ch R = 1 ,13530.4 ,243.1,244.5,245.9
XS GIS Cut Line= 2
     1950910.716      274531.857      1950619.05      274917.274
#Sta/Elev= 28
       0 2120.12    19.3 2112.54      29  2108.6    38.7 2103.71    48.3 2097.75
    67.7 2084.87    77.3  2078.9      87 2074.62    96.7 2072.43   106.3  2071.3
   110.6 2070.99     116  2070.6   125.6 2070.58   193.3 2072.12     232 2073.15
   280.3 2074.32   328.7 2075.15   367.3 2075.54   396.3 2076.08     406 2076.36
   415.7 2076.95   425.3 2078.61     435 2081.74   444.7 2085.77   454.3 2090.17
     464  2094.7   473.7 2099.33   483.3 2104.12
#Mann= 3 , 0 , 0
       0      .1       0   110.6    .045       0   125.6      .1       0
Bank Sta=110.6,125.6
XS Rating Curve= 0 ,0
Exp/Cntr=0.3,0.1

Type RM Length L Ch R = 1 ,13285.9 ,341.8,340.8,339.6
XS GIS Cut Line= 2
     1950733.633      274386.024     1950421.133       274758.42
#Sta/Elev= 30
       0 2121.79    19.4 2114.76    48.6 2102.62    58.3  2098.2    68.1 2093.22
    77.8 2087.52    87.5 2080.84    97.2 2073.72     107 2068.85   116.7  2068.1
   136.1 2069.25   145.8 2069.54   162.9  2069.7   184.7 2069.36   213.9 2068.59
   223.6 2068.66   243.1 2069.61   252.8  2069.9   272.2 2069.91   301.4  2069.4
     350 2068.14   369.5  2067.9   388.9 2068.02   398.6 2068.27   408.4 2069.06
   418.1 2071.32   427.8  2075.8   437.5 2081.32     457 2092.71   486.1 2110.22
#Mann= 3 , 0 , 0
       0      .1       0   162.9    .045       0   184.7      .1       0
Bank Sta=162.9,184.7
XS Rating Curve= 0 ,0
Exp/Cntr=0.3,0.1

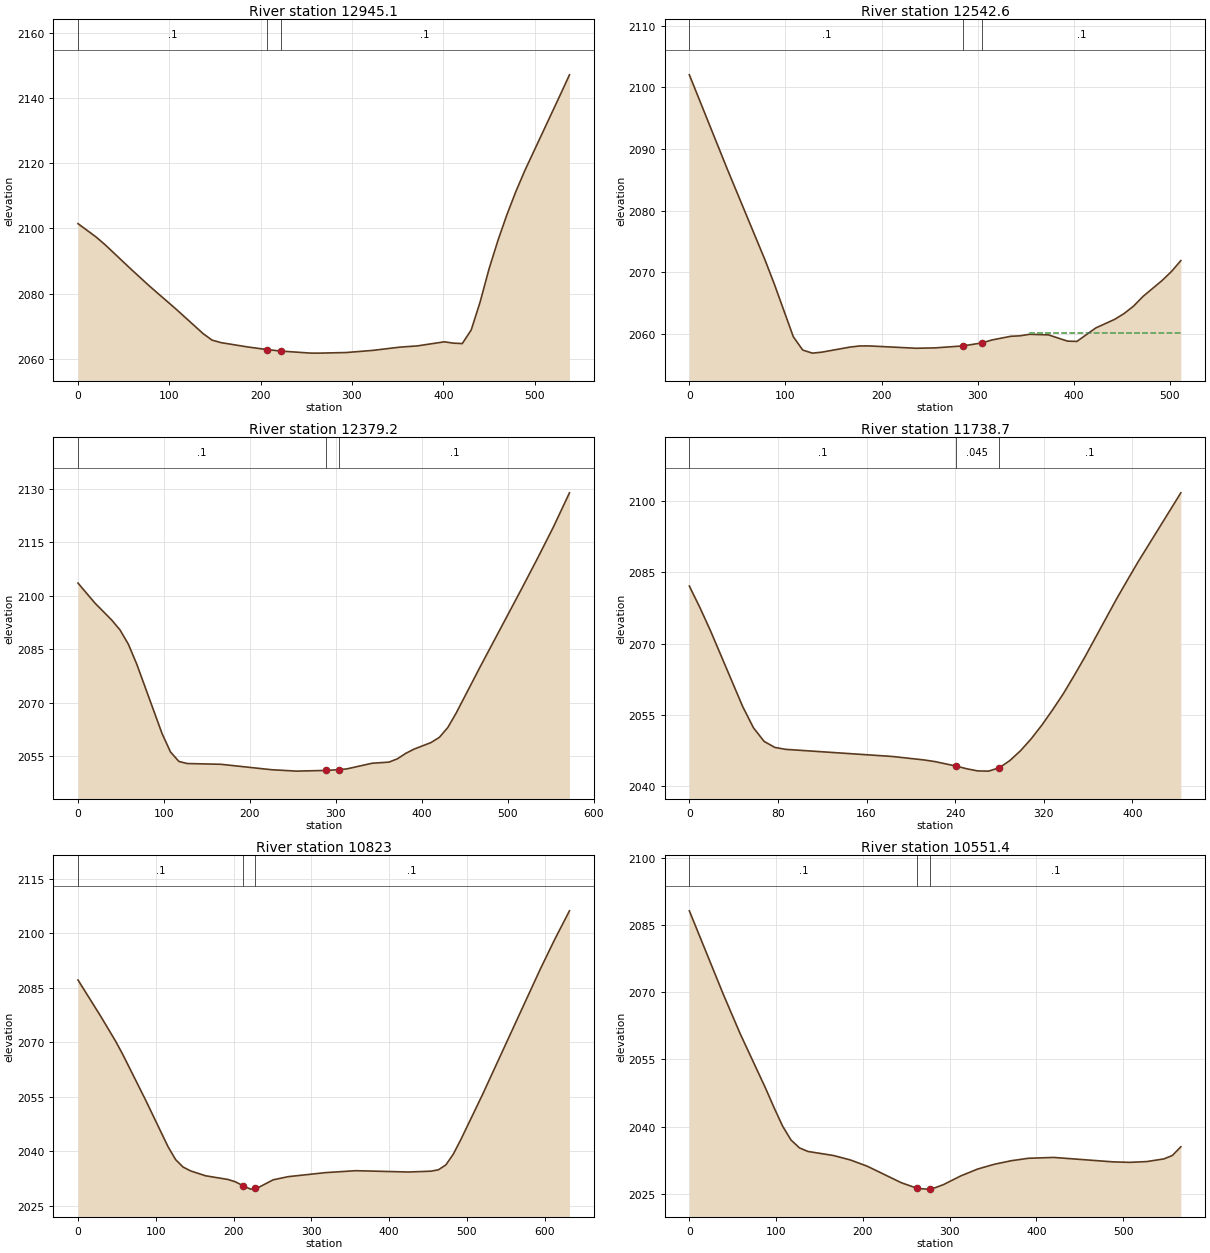
Type RM Length L Ch R = 1 ,12945.1 ,394.5,402.5,410.5
XS GIS Cut Line= 2
     1950461.752      274195.068     1950138.836      274625.623
#Sta/Elev= 30
       0 2101.44    19.6 2097.39    29.4 2095.05    58.7 2087.32    78.3 2082.29
   107.6 2075.18     137 2067.73   146.8 2065.73   156.6 2064.96   185.9 2063.63
   206.9 2062.83   221.9 2062.38   254.4 2061.75   264.2 2061.74   293.6 2061.92
   322.9 2062.58   352.3 2063.57   371.8 2063.96   401.2 2065.21     411  2064.8
   420.8 2064.67   430.6 2068.84   440.3 2077.37   450.1 2087.54   459.9 2096.31
   469.7 2104.19   479.5 2111.29   489.3  2117.7   528.4  2141.1   538.2 2147.06
#Mann= 3 , 0 , 0
       0      .1       0   206.9    .045       0   221.9      .1       0
Bank Sta=206.9,221.9
XS Rating Curve= 0 ,0
Exp/Cntr=0.3,0.1

Type RM Length L Ch R = 1 ,12542.6 ,161.8,163.4,164.9
XS GIS Cut Line= 2
     1950280.508      273974.566     1949848.216      274248.003
#Sta/Elev= 30
       0 2102.05    39.4 2086.78    78.7 2072.02    88.5 2068.06   108.2 2059.54
     118 2057.38   127.9 2056.88   137.7 2057.03   167.2 2057.86   177.1 2058.04
   186.9 2058.05   236.1 2057.67   255.8 2057.73   285.3 2058.06   304.9 2058.55
   314.8 2059.01   334.4 2059.61   344.3 2059.69   354.1 2059.94   373.8 2059.84
   393.5 2058.83   403.3 2058.78     423 2060.97   442.6 2062.36   452.5 2063.31
   462.3 2064.51   472.2 2066.09   491.8 2068.64   501.7 2070.12   511.5  2071.9
#Mann= 3 , 0 , 0
       0      .1       0   285.3    .045       0   304.9      .1       0
#XS Ineff= 2 , 0
                          354.08         2060.18
Permanent Ineff=
       F       F
Bank Sta=285.3,304.9
XS Rating Curve= 0 ,0
Exp/Cntr=0.3,0.1

Type RM Length L Ch R = 1 ,12379.2 ,635.5,640.5,645.5
XS GIS Cut Line= 3
     1950197.863      273858.262     1949819.391      274063.123
     1949683.975       274104.79
#Sta/Elev= 30
       0 2103.52    19.6 2097.94    39.1 2093.19    48.9 2090.38    58.7 2086.34
    68.5 2080.71    97.8 2061.33   107.6 2056.16   117.4 2053.48   127.2 2052.89
   166.3 2052.68     225 2051.16   254.3 2050.76   289.2 2050.96   304.2 2051.18
     313 2051.39   342.3 2052.97   361.9 2053.29   371.7 2054.21   381.5 2055.75
   391.2 2056.94   410.8 2058.77   420.6 2060.24   430.4    2063   439.8  2066.9
   468.1 2080.04   515.4  2101.5   534.3 2110.22   553.2  2119.2     572 2128.84
#Mann= 3 , 0 , 0
       0      .1       0   289.2    .045       0   304.2      .1       0
Bank Sta=289.2,304.2
XS Rating Curve= 0 ,0
Exp/Cntr=0.3,0.1

Type RM Length L Ch R = 1 ,11738.7 ,908.8,915.7,920.4
XS GIS Cut Line= 2
     1949901.536      273368.822     1949475.641      273493.679
#Sta/Elev= 28
       0 2082.11     9.6 2077.56    19.3  2072.6    48.2 2056.77    57.9 2052.32
    67.5 2049.47    77.2  2048.2    86.8  2047.8   183.3  2046.3   212.3 2045.56
   221.9 2045.22   240.4  2044.3   250.8  2043.7   260.5 2043.26   270.2 2043.22
   279.8 2043.92   289.4 2045.44   299.1 2047.52   308.7 2050.02   318.4 2052.92
     328  2056.1   337.7 2059.49   347.3 2063.23     357 2067.14   385.9 2079.47
   395.6 2083.38   405.2 2087.19   443.8  2101.7
#Mann= 3 , 0 , 0
       0      .1       0   240.4    .045       0   279.8      .1       0
Bank Sta=240.4,279.8
XS Rating Curve= 0 ,0
Exp/Cntr=0.3,0.1

Type RM Length L Ch R = 1 ,10823   ,272.4,271.6,272.4
XS GIS Cut Line= 3
     1949845.687      272543.043      1949364.53      272580.484
     1949222.169      272625.623
#Sta/Elev= 30
       0 2087.12      29 2077.21    48.3 2070.32    57.9 2066.51    86.9 2054.12
   115.8 2041.27   125.5 2037.73   135.1 2035.68   144.8 2034.61   164.1 2033.27
     193 2032.25   202.7 2031.59   212.6 2030.48     222  2029.6   227.6 2029.83
   231.6    2030     251 2032.16   270.3 2033.03   318.5 2034.14   357.1 2034.67
   424.7 2034.31   453.6 2034.53   463.3  2034.9     473 2036.25   482.6 2039.22
     492 2043.09     520 2055.52   594.6 2090.17   613.3  2098.4     632 2106.14
#Mann= 3 , 0 , 0
       0      .1       0   212.6    .045       0   227.6      .1       0
Bank Sta=212.6,227.6
XS Rating Curve= 0 ,0
Exp/Cntr=0.3,0.1

Type RM Length L Ch R = 1 ,10551.4 ,489,486.5,484.1
XS GIS Cut Line= 2
     1949865.633      272295.708     1949299.157      272307.676
#Sta/Elev= 30
       0 2088.11    39.1 2069.51    58.6  2060.7    87.9 2048.53    97.7 2044.19
   107.5  2040.1   117.2 2036.99     127 2035.23   136.8 2034.44   166.1 2033.54
   185.6 2032.55   205.2 2031.14   244.2 2027.48   262.8 2026.21   273.5 2026.04
   277.8 2026.18   283.3 2026.35   293.1 2027.06   312.6 2028.96   332.2 2030.51
   351.7 2031.59   371.2 2032.38   390.8 2032.92   420.1 2033.11   488.4 2032.12
     508 2032.01   527.5 2032.19   547.1 2032.78   556.8 2033.54   566.6 2035.48
#Mann= 3 , 0 , 0
       0      .1       0   262.8    .045       0   277.8      .1       0
Bank Sta=262.8,277.8
XS Rating Curve= 0 ,0
Exp/Cntr=0.3,0.1

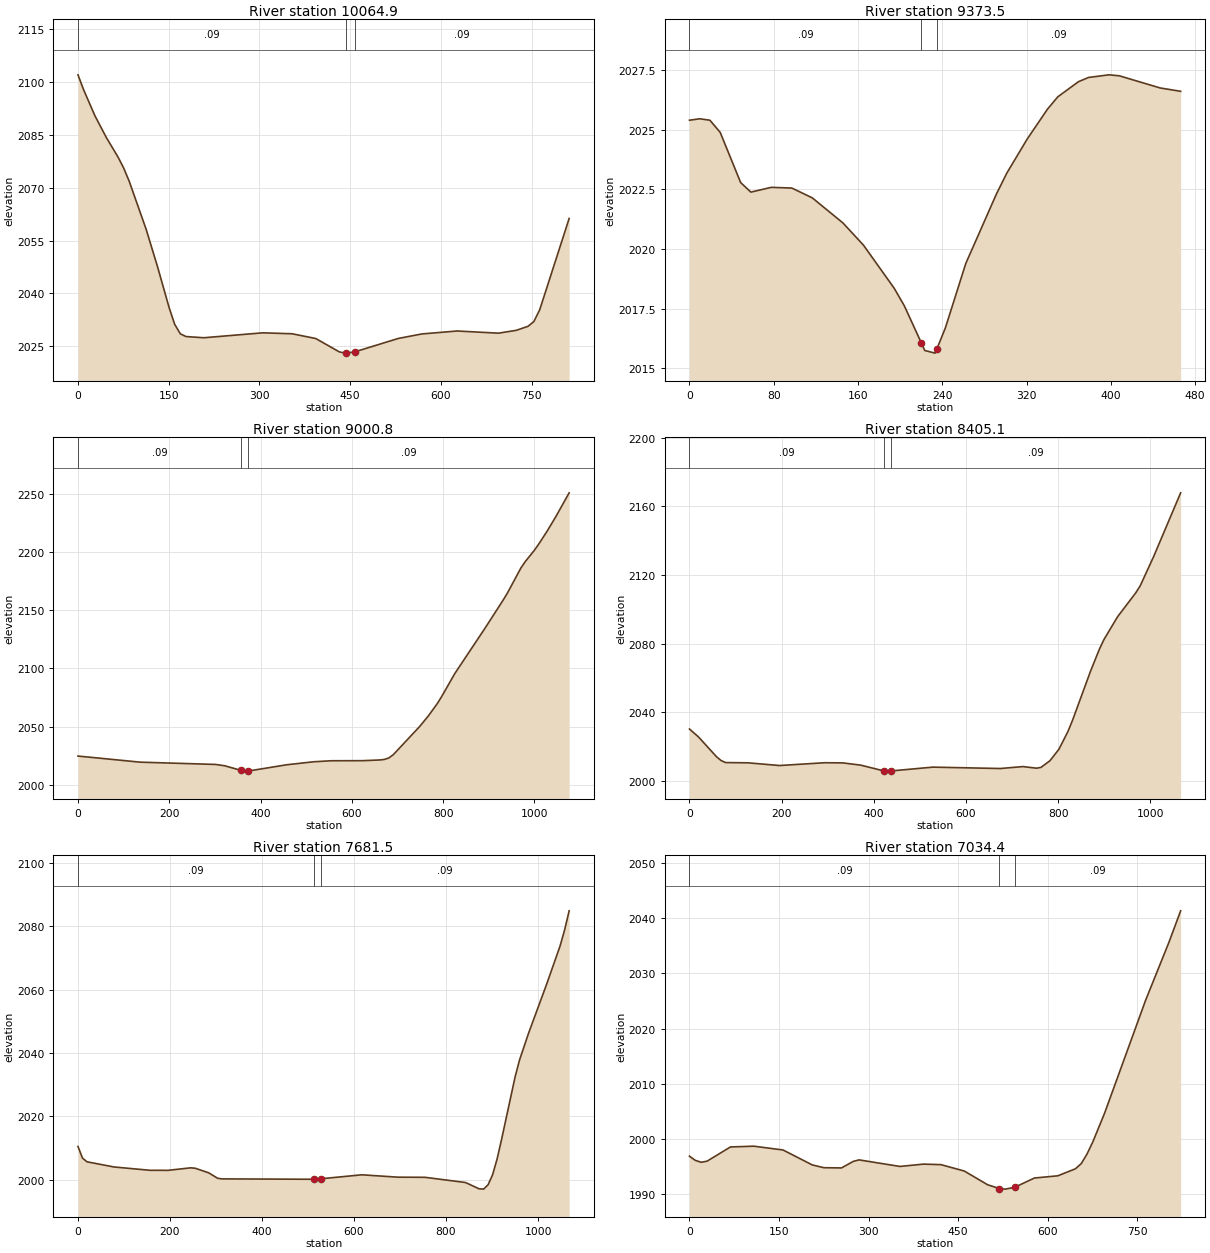
Type RM Length L Ch R = 1 ,10064.9 ,697.1,691.4,682.7
XS GIS Cut Line= 3
     1949861.058      271820.068     1949683.975      271844.373
     1949055.811      271924.706
#Sta/Elev= 30
       0 2102.09     9.4 2097.82    28.2 2090.39      47 2084.24    65.8 2078.85
    75.3  2075.7    84.7 2071.85   112.9 2058.09   131.7 2047.45   150.5 2036.05
   159.9 2031.18   169.3 2028.47   178.7 2027.71     208 2027.37   305.4 2028.77
   354.1  2028.5   393.1 2027.15   432.1 2023.35   441.8    2023   442.4    2023
   457.4 2023.35   529.5 2027.17   568.4 2028.45   626.9 2029.29   695.1 2028.67
   724.3 2029.47   743.8  2030.6   753.6 2031.96   763.3 2035.31     812 2061.28
#Mann= 3 , 0 , 0
       0     .09       0   442.4    .045       0   457.4     .09       0
Bank Sta=442.4,457.4
XS Rating Curve= 0 ,0
Exp/Cntr=0.3,0.1

Type RM Length L Ch R = 1 ,9373.5  ,373,372.7,373.5
XS GIS Cut Line= 2
     1949618.002      271219.373     1949222.169      271465.901
#Sta/Elev= 30
       0 2025.39     9.7 2025.45    19.4 2025.39    29.2 2024.88    48.6 2022.78
    58.3 2022.38    77.7 2022.58    97.2 2022.55   116.6 2022.14   145.7 2021.09
   165.2 2020.16   194.3 2018.36     204 2017.62     220 2016.08   223.4 2015.75
   233.2 2015.64     235 2015.83   242.9 2016.69   262.3 2019.39   291.4  2022.3
   301.2 2023.17   320.6  2024.6     340 2025.86   349.7 2026.37   369.2    2027
   378.9 2027.18   398.3 2027.29     408 2027.25   446.9 2026.74   466.3  2026.6
#Mann= 3 , 0 , 0
       0     .09       0     220    .045       0     235     .09       0
Bank Sta=220,235
XS Rating Curve= 0 ,0
Exp/Cntr=0.3,0.1

Type RM Length L Ch R = 1 ,9000.8  ,576.5,595.7,605.5
XS GIS Cut Line= 3
     1949631.891      270879.095     1948996.475      271149.929
      1948614.53      271202.012
#Sta/Elev= 30
       0 2024.77   136.2 2019.54   301.6 2017.57     321 2016.48   357.9 2012.43
   369.7 2011.84   372.9 2011.91   457.2 2017.29   515.6 2019.84   554.5 2020.73
   622.6  2020.8   661.5 2021.42   671.3 2021.86     681 2023.13   690.7 2025.88
   748.6 2050.11   767.8 2059.27   787.1 2069.69   796.7 2075.74   825.6 2095.53
   893.1 2135.23   931.6 2158.63   941.3 2164.89   970.2 2185.96   979.8 2191.52
   999.1  2200.9  1008.8 2206.21    1028 2217.79  1047.3 2230.39  1076.2 2250.63
#Mann= 3 , 0 , 0
       0     .09       0   357.9    .045       0   372.9     .09       0
Bank Sta=357.9,372.9
XS Rating Curve= 0 ,0
Exp/Cntr=0.3,0.1

Type RM Length L Ch R = 1 ,8405.1  ,733.4,723.6,718.8
XS GIS Cut Line= 2
     1949610.723      270489.244     1948545.185      270508.515
#Sta/Elev= 30
       0 2030.32    19.6 2025.69    58.7 2014.16    68.4 2011.99    78.2 2010.76
   127.1  2010.6   195.5 2009.03   293.3 2010.66   332.4 2010.57   371.5 2009.26
   421.4 2005.92   430.2 2005.77   436.4 2005.85     528  2008.1   674.6 2007.29
   723.5 2008.42   752.8 2007.48   762.6 2007.94   782.2 2011.85   801.7 2018.56
   821.3 2028.95   831.1 2035.38   870.2 2064.01   889.7 2076.99   899.5 2082.52
   928.8 2095.68   967.9 2109.49   977.7 2113.58    1007  2130.7  1065.7 2167.89
#Mann= 3 , 0 , 0
       0     .09       0   421.4    .045       0   436.4     .09       0
Bank Sta=421.4,436.4
XS Rating Curve= 0 ,0
Exp/Cntr=0.3,0.1

Type RM Length L Ch R = 1 ,7681.5  ,645.5,647.1,642.6
XS GIS Cut Line= 2
     1949765.748      270220.029     1948763.836      269851.318
#Sta/Elev= 30
       0 2010.53     9.8 2006.87    19.6 2005.69    78.4 2004.06   156.7 2003.01
   195.9    2003   244.9 2003.79   254.7 2003.66     284 2002.23   303.6 2000.49
   313.4  2000.3   512.8 2000.18   527.8 2000.33   617.1 2001.59   695.4 2000.84
   754.2  2000.8   842.3 1999.16   871.7 1997.18   881.5 1997.07   891.3 1998.43
   901.1 2001.57   910.9 2006.53   920.7 2012.76   950.1 2032.48   959.9 2037.89
   979.4 2046.27  1018.6 2061.71    1048 2073.85  1057.8  2078.9  1067.6 2084.88
#Mann= 3 , 0 , 0
       0     .09       0   512.8    .045       0   527.8     .09       0
Bank Sta=512.8,527.8
XS Rating Curve= 0 ,0
Exp/Cntr=0.3,0.1

Type RM Length L Ch R = 1 ,7034.4  ,340.2,333.9,328.1
XS GIS Cut Line= 2
      1949881.59       269830.34     1949139.586      269475.295
#Sta/Elev= 30
       0 1996.82     9.8 1996.05    19.6 1995.71    29.4  1995.9    68.6 1998.49
   107.7 1998.63   156.7 1997.94   205.6 1995.23   225.2 1994.72   254.6 1994.68
   274.2 1995.86     284 1996.14   352.5 1994.95   391.7 1995.37   421.1 1995.28
   460.2 1994.12   499.4 1991.62     519 1990.94   528.8 1990.83   544.6 1991.16
   577.8 1992.85   616.9 1993.25   646.3 1994.52   656.1 1995.46   665.9 1997.23
   675.7 1999.46   695.3 2004.65   763.8  2025.1     803 2035.67   822.6 2041.38
#Mann= 3 , 0 , 0
       0     .09       0     519    .045       0   544.6     .09       0
Bank Sta=519,544.6
XS Rating Curve= 0 ,0
Exp/Cntr=0.3,0.1