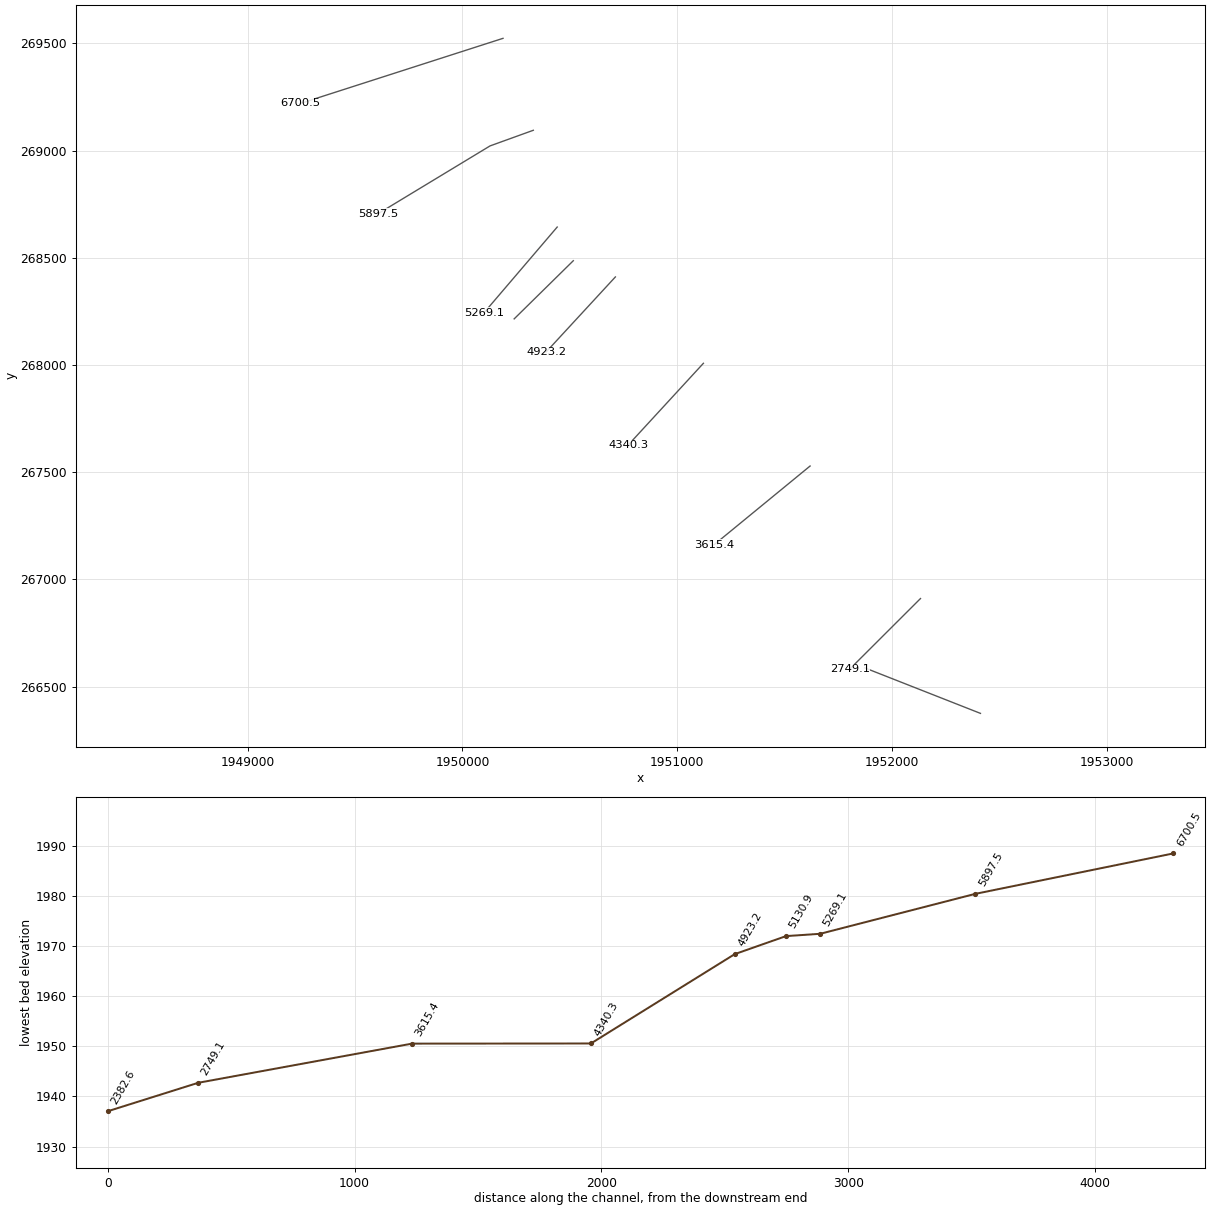
HEC-RAS study HORSSHOERN.prj: HORSSHOERN

--- HORSSHOERN.g01 (geometry) --- (continued)

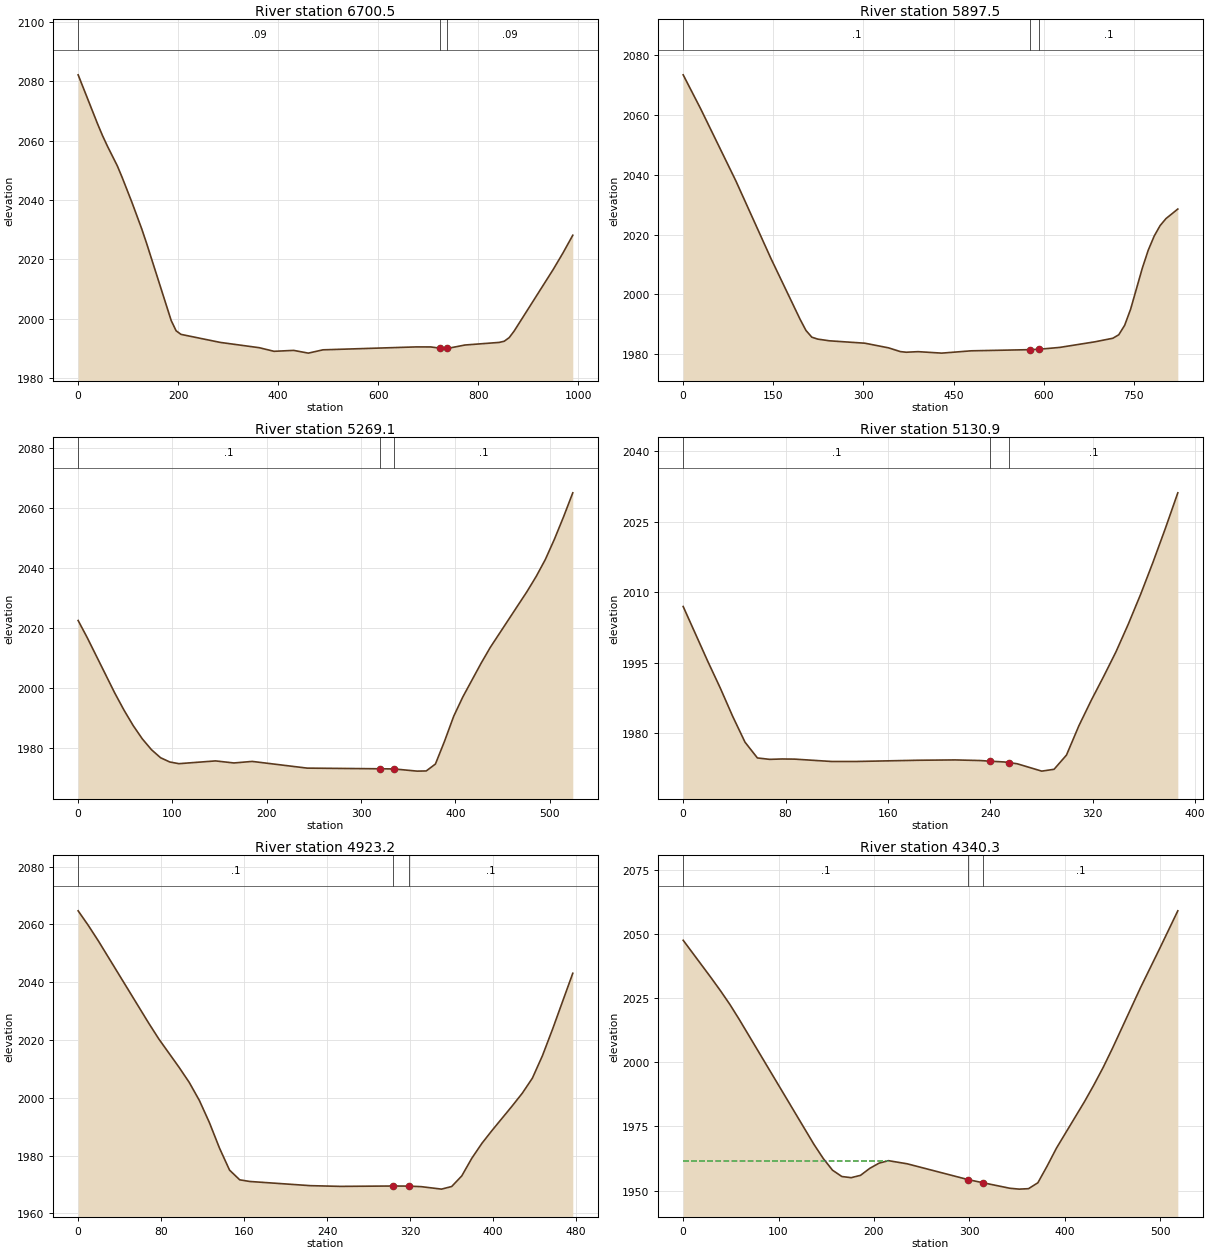
Type RM Length L Ch R = 1 ,6700.5  ,791.1,803.1,813.1
XS GIS Cut Line= 2
     1950188.764      269523.166     1949247.296      269219.982
#Sta/Elev= 30
       0  2082.1    39.2 2065.45      49 2061.55    58.8 2058.02    78.3 2051.49
    88.1 2047.55   107.7 2039.13   127.3 2030.21   137.1  2025.3   186.1 1999.42
   195.9 1995.99   205.6 1994.78     284 1992.08   362.3 1990.29   391.7 1989.08
   430.9 1989.39   460.3 1988.47   489.6 1989.58   675.7 1990.56   705.1 1990.55
   723.1 1990.15   738.1 1990.04   773.6  1991.2   842.2 1992.08     852 1992.47
   861.8 1993.66   871.6 1995.83   949.9  2016.6   969.5 2022.17   989.1 2028.13
#Mann= 3 , 0 , 0
       0     .09       0   723.1    .045       0   738.1     .09       0
Bank Sta=723.1,738.1
XS Rating Curve= 0 ,0
Exp/Cntr=0.3,0.1

Type RM Length L Ch R = 1 ,5897.5  ,622.4,628.4,635.3
XS GIS Cut Line= 3
     1950329.808      269094.373     1950128.419      269021.457
     1949607.586      268705.484
#Sta/Elev= 30
       0 2073.32    29.2 2061.94    87.6 2037.95     146 2012.04   194.7 1991.66
   204.4 1987.97   214.2 1985.72     224 1985.08   243.7 1984.51   302.6 1983.71
   341.9 1982.16   361.6 1980.91   371.4  1980.7     391 1980.89   430.4  1980.4
   479.5 1981.17   577.8 1981.56   592.8  1981.7   626.9 1982.31   685.8 1984.19
   715.3 1985.37   725.1 1986.53   734.9 1989.68   744.8 1995.05   764.4 2008.83
   774.2 2014.79   784.1 2019.49   793.9 2022.97   803.7 2025.32   823.4 2028.51
#Mann= 3 , 0 , 0
       0      .1       0   577.8    .045       0   592.8      .1       0
Bank Sta=577.8,592.8
XS Rating Curve= 0 ,0
Exp/Cntr=0.3,0.1

Type RM Length L Ch R = 1 ,5269.1  ,140,138.2,136.2
XS GIS Cut Line= 2
     1950440.919      268642.984     1950100.641      268243.679
#Sta/Elev= 30
       0 2022.56     9.7 2016.82    38.9 1998.39    48.6 1992.76    58.3 1987.64
      68  1983.2    77.7 1979.59    87.4  1976.9    97.2 1975.48   106.9 1974.92
   145.7 1975.84   165.2 1975.16   184.6 1975.67   242.9 1973.44   319.9 1973.22
   334.9 1973.17   359.5 1972.44   369.2  1972.5   378.9  1974.8   388.6 1982.41
   398.3  1990.7     408 1997.15   427.5 2008.42   437.2 2013.67     476 2032.18
   485.8 2037.24   495.5 2042.88   505.2 2049.68   514.9 2057.14   524.6 2065.06
#Mann= 3 , 0 , 0
       0      .1       0   319.9    .045       0   334.9      .1       0
Bank Sta=319.9,334.9
XS Rating Curve= 0 ,0
Exp/Cntr=0.3,0.1

Type RM Length L Ch R = 1 ,5130.9  ,206.7,207.7,208.9
XS GIS Cut Line= 2
     1950515.884      268485.956     1950240.624      268214.686
#Sta/Elev= 30
       0 2006.96    19.3 1995.26      29 1989.63    38.6 1983.67    48.3 1978.14
      58 1974.78    67.6 1974.48    77.3 1974.56      87 1974.53   115.9 1974.03
   135.3 1974.03   183.6 1974.29   212.6 1974.36   231.9 1974.23   239.5  1974.1
   251.2 1973.92   254.5 1973.79   260.9 1973.55   280.2 1971.98   289.8 1972.37
   299.5 1975.39   309.2 1981.62   318.8 1986.99   328.5 1992.07   338.2 1997.34
   347.8 2003.21   357.5 2009.58   367.1 2016.36   376.8 2023.57   386.5 2031.11
#Mann= 3 , 0 , 0
       0      .1       0   239.5    .045       0   254.5      .1       0
Bank Sta=239.5,254.5
XS Rating Curve= 0 ,0
Exp/Cntr=0.3,0.1

Type RM Length L Ch R = 1 ,4923.2  ,583.1,582.9,583
XS GIS Cut Line= 2
     1950711.752      268410.345     1950388.836      268059.651
#Sta/Elev= 30
       0  2064.7     9.7  2059.7    19.5 2054.28    68.1 2025.78    77.8 2020.33
    97.3 2010.53     107 2005.36   116.8  1999.1   126.5 1991.42   136.2 1982.61
   145.9 1974.98   155.7 1971.61   165.4 1971.04   223.8 1969.59     253 1969.34
   303.4 1969.47   318.4 1969.44   330.8 1969.24   350.2 1968.39     360  1969.3
   369.7 1972.96   379.4 1979.08   389.2 1984.27   398.9  1988.7   418.4 1997.21
   428.1 2001.61   437.8 2006.82   447.5  2014.6   457.3 2023.83   476.7 2043.09
#Mann= 3 , 0 , 0
       0      .1       0   303.4    .045       0   318.4      .1       0
Bank Sta=303.4,318.4
XS Rating Curve= 0 ,0
Exp/Cntr=0.3,0.1

Type RM Length L Ch R = 1 ,4340.3  ,731.2,724.9,713.1
XS GIS Cut Line= 2
     1951121.475      268007.568      1950770.78      267625.623
#Sta/Elev= 30
       0 2047.62    29.4 2032.93    39.1 2027.93    48.9 2022.62    58.7  2016.8
     137 1968.07   146.8 1962.54   156.5 1957.97   166.3 1955.49   176.1 1955.04
   185.9 1955.95   195.7  1958.7   205.4 1960.71   215.2 1961.67   234.8 1960.45
     299 1954.25     314 1953.08   342.4 1950.91   352.2 1950.57     362 1950.75
   371.8 1953.05   381.6 1959.62   391.3 1966.57   420.7 1984.71   430.5 1991.19
   440.3 1998.07     450 2005.48   479.4 2029.14     499 2044.02   518.5  2059.1
#Mann= 3 , 0 , 0
       0      .1       0     299    .045       0     314      .1       0
#XS Ineff= 2 , 0
          215.49 1961.68
Permanent Ineff=
       F       F
Bank Sta=299,314
XS Rating Curve= 0 ,0
Exp/Cntr=0.3,0.1

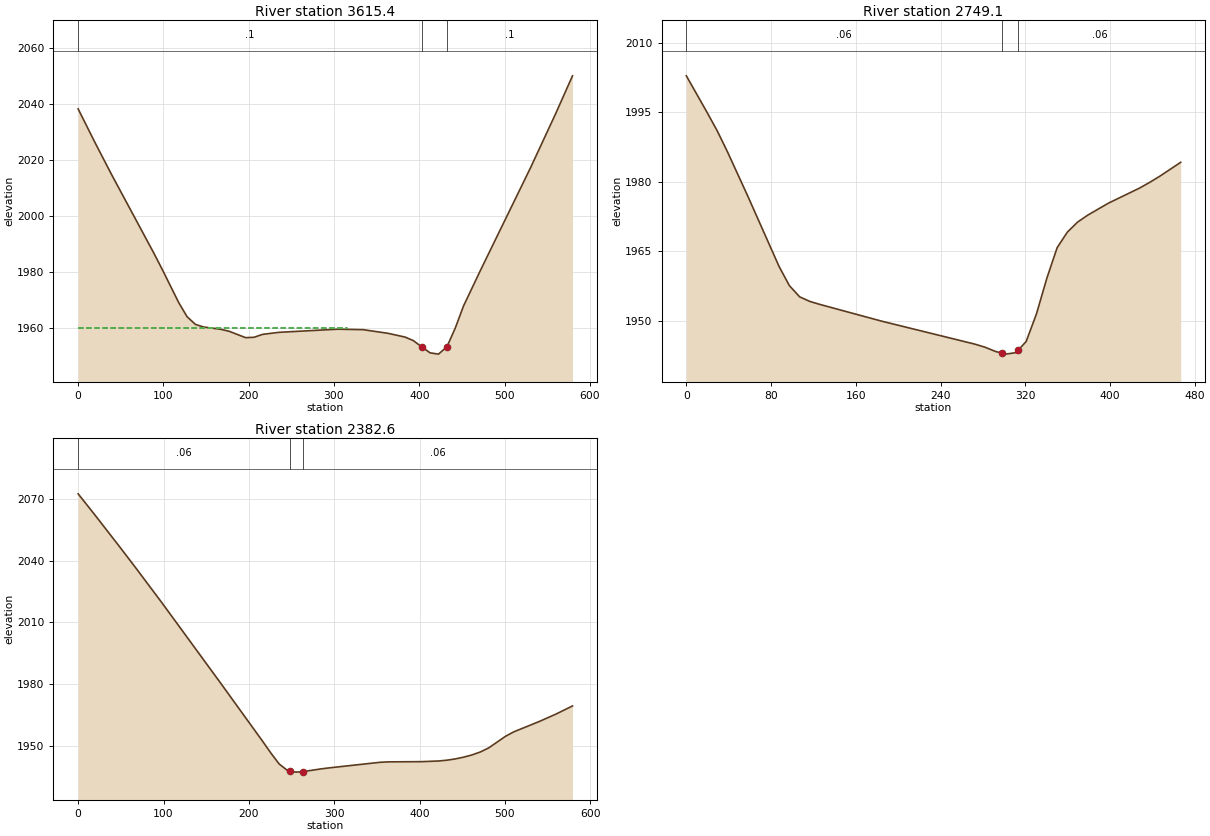
Type RM Length L Ch R = 1 ,3615.4  ,864,866.3,868.5
XS GIS Cut Line= 2
     1951618.002      267528.401     1951170.086      267160.345
#Sta/Elev= 30
       0 2038.25    19.6  2026.3    39.3 2014.71    88.4 1986.87    98.3 1981.04
   117.9    1969   127.7 1963.94   137.6 1961.16   147.4 1960.22     167 1959.44
   176.9 1958.73   196.5 1956.42   206.4 1956.57   216.2  1957.6   235.8 1958.34
   304.6 1959.46   334.1 1959.29   363.6 1957.97   383.2 1956.65     393 1955.39
   402.9 1953.14   412.7    1951   422.5 1950.54   432.4 1953.13   442.2 1959.83
     452 1967.82   471.6 1980.39   530.6 2017.26   560.1 2036.63   579.7 2050.06
#Mann= 3 , 0 , 0
       0      .1       0   402.9    .045       0   432.4      .1       0
#XS Ineff= 2 , 0
          315.21 1959.86
Permanent Ineff=
       F       F
Bank Sta=402.9,432.4
XS Rating Curve= 0 ,0
Exp/Cntr=0.3,0.1

Type RM Length L Ch R = 1 ,2749.1  ,394.4,366.4,338
XS GIS Cut Line= 2
     1952131.891      266910.345      1951802.03      266580.484
#Sta/Elev= 30
       0  2002.9    19.4 1995.07    29.2 1990.99    38.9 1986.43    58.3 1976.74
    87.5 1961.69    97.2 1957.56   106.9 1955.12   116.6 1954.12   126.3 1953.46
   184.6 1949.84   272.1  1944.9   281.8 1944.23   291.6 1943.32   298.1 1942.92
   301.3 1942.73     311 1943.05   313.1 1943.57   320.7 1945.47   330.4 1951.43
   340.2 1959.14   349.9 1965.74   359.6 1969.12   369.3 1971.29     379 1972.81
   398.5 1975.39   427.6 1978.62   437.3 1979.87   447.1 1981.24   466.5  1984.2
#Mann= 3 , 0 , 0
       0     .06       0   298.1    .045       0   313.1     .06       0
Bank Sta=298.1,313.1
XS Rating Curve= 0 ,0
Exp/Cntr=0.3,0.1

Type RM Length L Ch R = 1 ,2382.6  ,2378.7,2382.6,2386.8
XS GIS Cut Line= 2
     1952410.983      266374.709     1951872.235      266587.064
#Sta/Elev= 30
       0 2072.46    19.6 2062.22    49.1 2046.44    68.7 2035.78    98.2 2019.43
   166.9 1980.38   215.9  1952.2   225.8 1946.34   235.6 1940.97   245.4 1937.82
     248 1937.62   255.2 1937.06     263 1937.27   284.6 1938.64   294.4 1939.14
   353.3 1941.83   363.2 1942.05   402.4 1942.15     422 1942.47   431.9 1942.86
   441.7 1943.48   451.5 1944.33   461.3 1945.42   471.1 1946.86   480.9 1948.84
   500.6 1954.48   510.4 1956.67   539.8 1961.63   559.5 1965.25   579.1 1969.25
#Mann= 3 , 0 , 0
       0     .06       0     248    .045       0     263     .06       0
Bank Sta=248,263
XS Rating Curve= 0 ,0
Exp/Cntr=0.3,0.1

Chan Stop Cuts=-1
Use User Specified Reach Order=0
Composite Channel Slope=5